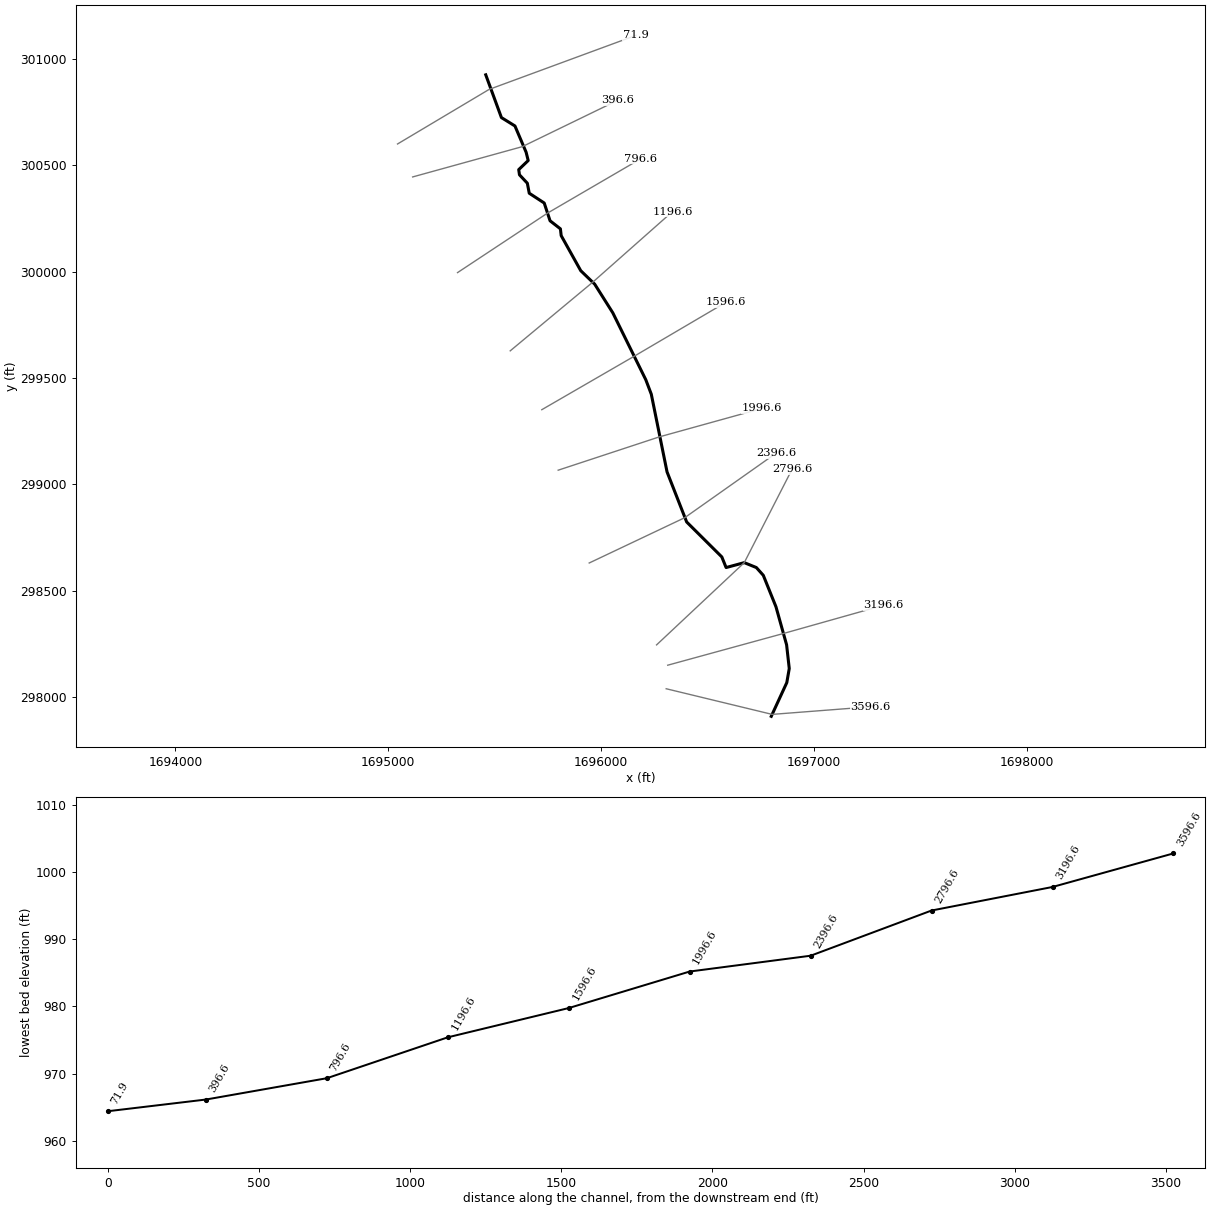
--- NewCr.prj (project) ---

Proj Title=NewCr
Current Plan=p01
Default Exp/Contr=0,0
English Units
Geom File=g01
Flow File=f01
Plan File=p01
BEGIN DESCRIPTION:
END DESCRIPTION:
DSS Export Rating Curves= 0
DSS Export Rating Curve Sorted= 0
DSS Export Volume Flow Curves= 0
DXF OffsetX= 0
DXF OffsetY= 0
DXF ScaleX= 0
DXF ScaleY= 0

--- NewCr.p01 (plan) ---

Plan Title=Floodplain
Program Version=4.00
Geom File=g01
Flow File=f01
K Sum by GR=0
Std Step Tol=0.01
Critical Tol=0.01
Num of Std Step Trials=20
Max Error Tol=0.3
Flow Tol Ratio=0.001
Split Flow NTrial=30
Split Flow Tol=0.02
Split Flow Ratio=0.02
Log Output Level=0
Friction Slope Method=1
Unsteady Friction Slope Method=2
Unsteady Bridges Friction Slope Method=1
Global Log Level=0
CheckData=False
Run HTab=0
Run UNet=0
Run PostProcess=0
UNET Theta=0
UNET Theta Warmup=0
UNET ZTol=0
UNET ZSATol=0
UNET MxIter=0
UNET MaxInSteps=0
UNET DtIC=0
UNET DtMin=0
UNET MaxCRTS=0
UNET WFStab=0
UNET SFStab=0
UNET WFX=0
UNET SFX=0
UNET DSS MLevel=0
UNET DZMax Abort=0
UNET Convert EG Bridges=0
UNET Use Existing IB Tables=0
UNET Froude Limit=0
UNET Froude Power=0
Write IC File=0
Echo Input=False
Echo Output=False
Write Detailed=0

--- NewCr.f01 (steady flow) ---

Flow Title=NFF Regression Equation
Program Version=4.00
Number of Profiles= 1
Profile Names=P100yr
River Rch & RM=NewCr,Main            ,3596.6
954.5188
River Rch & RM=NewCr,Main            ,396.6
1050.478
River Rch & RM=NewCr,Main            ,71.9
1057.102
Boundary for River Rch & Prof#=NewCr,Main            , 1
Up Type= 0
Dn Type= 3
Dn Slope=0.010129
DSS Import GetInterval= 0
DSS Import GetPeak= 0
DSS Import FillOption= 0

--- NewCr.g01 (geometry) ---

Geom Title=USGS 3m DEM
Program Version=4.00

River Reach=NewCr     ,Main
Reach XY= 30
     1696798.931      297910.890     1696871.892      298069.292
     1696883.411      298135.529     1696870.932      298246.890
     1696821.012      298425.449     1696761.492      298573.292
     1696728.851      298609.770     1696672.213      298632.810
     1696586.772      298609.771     1696566.610      298659.690
     1696401.493      298823.850     1696309.333      299059.048
     1696235.412      299423.852     1696209.493      299492.011
     1696054.508      299806.372     1695969.432      299941.039
     1695903.981      300004.210     1695812.053      300168.982
     1695808.423      300200.835     1695759.769      300238.736
     1695732.352      300322.200     1695662.059      300368.165
     1695653.055      300415.203     1695616.096      300454.717
     1695612.602      300479.043     1695657.086      300521.781
     1695647.278      300560.894     1695594.861      300684.139
     1695531.289      300723.519     1695457.658      300924.398

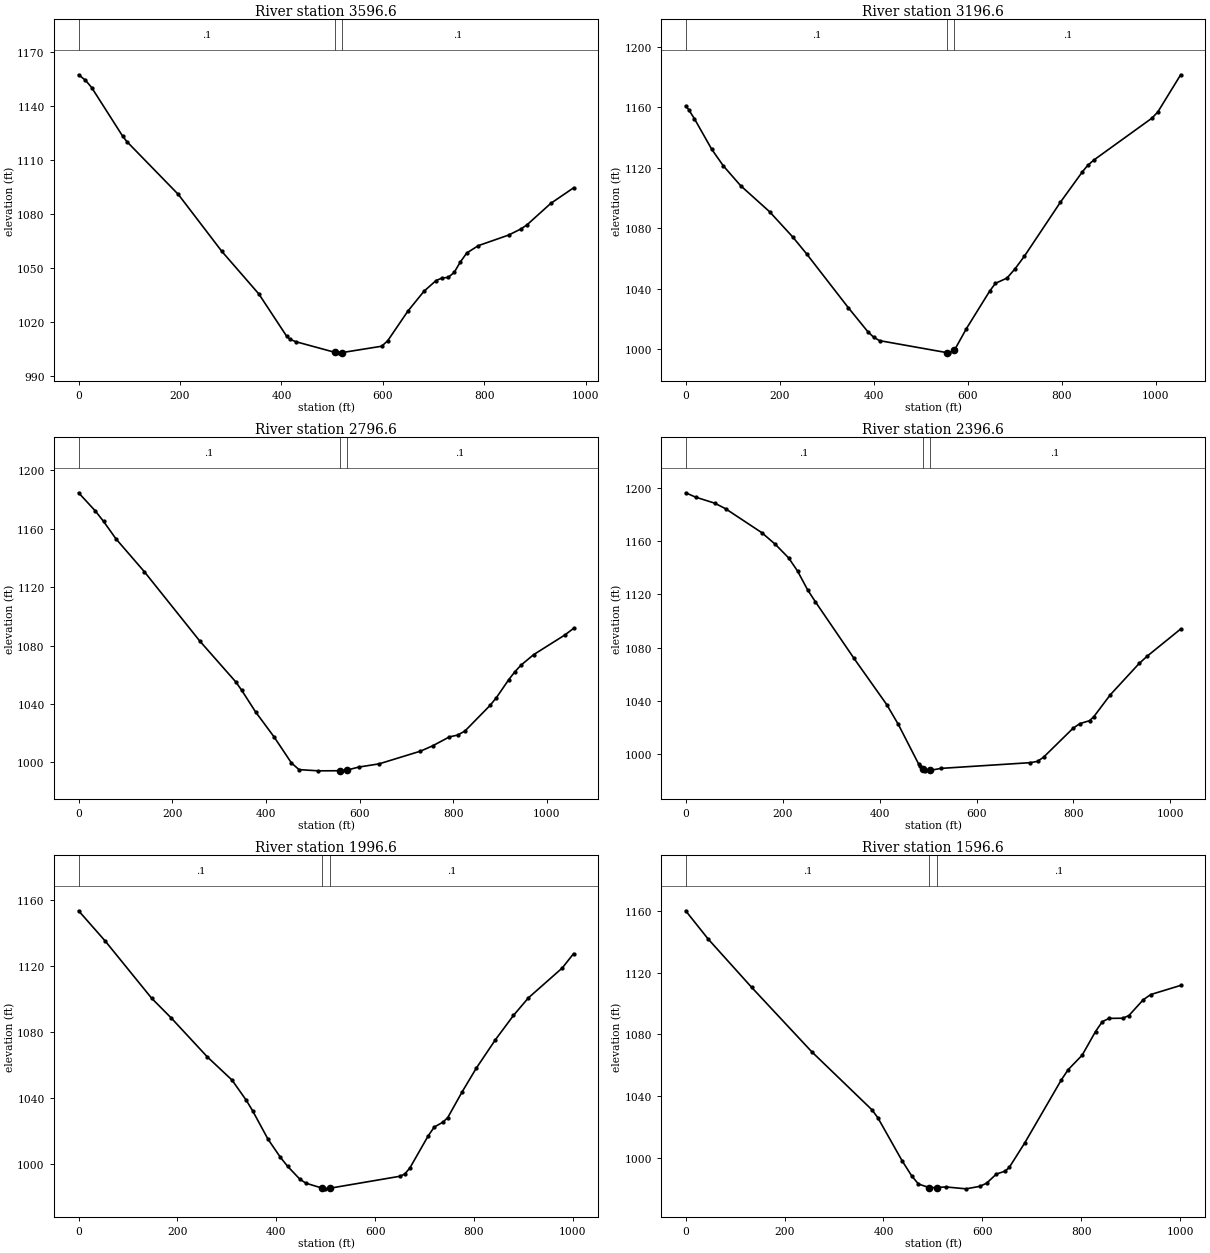
Type RM Length L Ch R = 1 ,3596.6,388.608,400,403.425
XS GIS Cut Line= 3
     1696305.344      298040.442     1696803.115      297919.972
     1697265.566      297955.788
#Sta/Elev= 30
       0 1157.48    13.5 1154.45    25.7 1150.39    86.8 1123.35    95.3 1120.26
   196.7 1090.87   282.1 1059.32   355.5 1035.46   410.0 1012.09   416.6 1010.27
   428.8 1008.90   504.6 1003.07   514.2 1002.74   519.6 1002.89   597.6 1006.42
   609.5 1009.47   649.1 1025.91   681.0 1037.02   704.8 1042.96   716.7 1044.39
   728.6 1044.71   740.5 1047.47   752.4 1053.18   765.3 1058.29   788.1 1062.39
   847.7 1068.26   871.5 1071.59   883.4 1073.79   931.0 1085.91   976.0 1094.57
#Mann= 3 , 0 , 0
       0     0.1       0   504.6   0.045       0   519.6     0.1       0
Bank Sta=   504.6,   519.6
Exp/Cntr=0.3,0.1

Type RM Length L Ch R = 1 ,3196.6,406.23,400,418.678
XS GIS Cut Line= 3
     1696312.469      298151.014     1696855.977      298299.958
     1697327.005      298432.697
#Sta/Elev= 30
       0 1160.91     6.2 1158.50    18.5 1152.46    55.4 1132.24    80.0 1121.31
   117.0 1108.15   178.5 1090.97   227.8 1074.27   257.1 1063.19   345.9 1027.59
   387.8 1011.60   400.1 1008.02   412.4 1005.81     556  997.86   560.2  997.75
     571  999.60   572.5  999.96   597.2 1013.77   646.5 1038.46   658.8 1043.65
   683.5 1047.14   701.0 1053.41   720.5 1061.60   797.2 1097.30   843.9 1117.35
   855.0 1121.55   868.5 1125.18   991.9 1152.81  1004.2 1156.82  1052.9 1181.44
#Mann= 3 , 0 , 0
       0     0.1       0     556   0.045       0     571     0.1       0
Bank Sta=     556,     571
Exp/Cntr=0.3,0.1

Type RM Length L Ch R = 1 ,2796.6,390.857,400,387.182
XS GIS Cut Line= 3
     1696260.096      298246.358     1696672.106      298632.801
     1696896.433      299071.005
#Sta/Elev= 30
       0 1184.65    36.0 1172.10    53.3 1165.04    80.0 1153.03   140.1 1130.73
   259.0 1083.06   335.9 1055.08   348.4 1049.38   377.9 1034.65   417.8 1017.34
   454.4  999.72   470.7  995.08   512.3  994.25   557.4  994.32   572.4  994.67
   597.8  996.80   641.9  999.04   730.2 1007.73   756.6 1011.45   791.9 1017.49
   809.6 1018.74   825.3 1021.55   878.6 1039.00   892.0 1044.22   918.7 1056.69
   932.0 1062.18   945.3 1066.73   972.0 1073.85  1038.7 1087.31  1057.2 1091.83
#Mann= 3 , 0 , 0
       0     0.1       0   557.4   0.045       0   572.4     0.1       0
Bank Sta=   557.4,   572.4
Exp/Cntr=0.3,0.1

Type RM Length L Ch R = 1 ,2396.6,402.81,400,392.211
XS GIS Cut Line= 3
     1695943.709      298631.170     1696392.041      298843.782
     1696820.897      299146.478
#Sta/Elev= 30
       0 1196.32    20.5 1193.05    59.9 1188.52    82.2 1184.36   156.9 1166.40
   184.6 1157.73   212.3 1147.46   230.8 1137.56   251.6 1123.39   267.7 1114.41
   347.4 1071.89   414.7 1037.29   438.7 1022.37   480.4  992.76   483.3  990.94
   488.7  989.05   493.6  987.53   503.7  987.83   526.5  989.37   711.3  993.68
   725.8  994.66   738.2  997.75   799.1 1019.50   813.0 1022.95   833.2 1025.20
   842.1 1028.26   875.8 1044.57   935.4 1068.13   952.4 1073.75  1021.1 1094.01
#Mann= 3 , 0 , 0
       0     0.1       0   488.7   0.045       0   503.7     0.1       0
Bank Sta=   488.7,   503.7
Exp/Cntr=0.3,0.1

Type RM Length L Ch R = 1 ,1996.6,395.344,400,405.887
XS GIS Cut Line= 3
     1695797.995      299067.151     1696273.271      299223.648
     1696756.254      299357.518
#Sta/Elev= 30
       0 1153.74    54.0 1135.34   147.9 1100.69   187.5 1088.73   260.4 1065.19
   310.4 1051.13   339.4 1038.82   352.1 1032.50   383.4 1015.20   408.0 1004.43
   422.9  998.84   447.9  990.97   460.4  988.55   492.9  985.62   497.9  985.18
   507.9  985.53   650.5  992.82   660.2  994.21   670.4  997.89   707.4 1017.30
   719.7 1022.66   737.3 1025.60   747.0 1028.39   775.9 1043.89   804.8 1058.37
   843.4 1075.57   879.9 1090.29   910.2 1100.97   978.4 1118.99  1001.6 1127.76
#Mann= 3 , 0 , 0
       0     0.1       0   492.9   0.045       0   507.9     0.1       0
Bank Sta=   492.9,   507.9
Exp/Cntr=0.3,0.1

Type RM Length L Ch R = 1 ,1596.6,396.159,400,404.377
XS GIS Cut Line= 3
     1695720.937      299351.259     1696154.156      299601.931
     1696585.610      299855.594
#Sta/Elev= 30
       0 1160.15    45.6 1141.78   133.3 1110.52   254.9 1068.70   376.6 1031.05
   388.5 1025.94   437.4  998.11   457.1  988.14   470.8  982.86     493  980.50
     508  980.60   525.8  980.99   567.1  979.75   594.7  981.36   608.4  983.37
   628.3  989.33   645.7  991.21   654.3  993.61   685.5 1009.44   759.9 1050.56
   773.7 1057.14   801.8 1066.46   828.8 1081.79   842.6 1088.23   856.4 1090.34
   883.9 1090.44   896.3 1092.18   925.2 1102.38   940.5 1105.81  1001.0 1111.73
#Mann= 3 , 0 , 0
       0     0.1       0     493   0.045       0     508     0.1       0
Bank Sta=     493,     508
Exp/Cntr=0.3,0.1

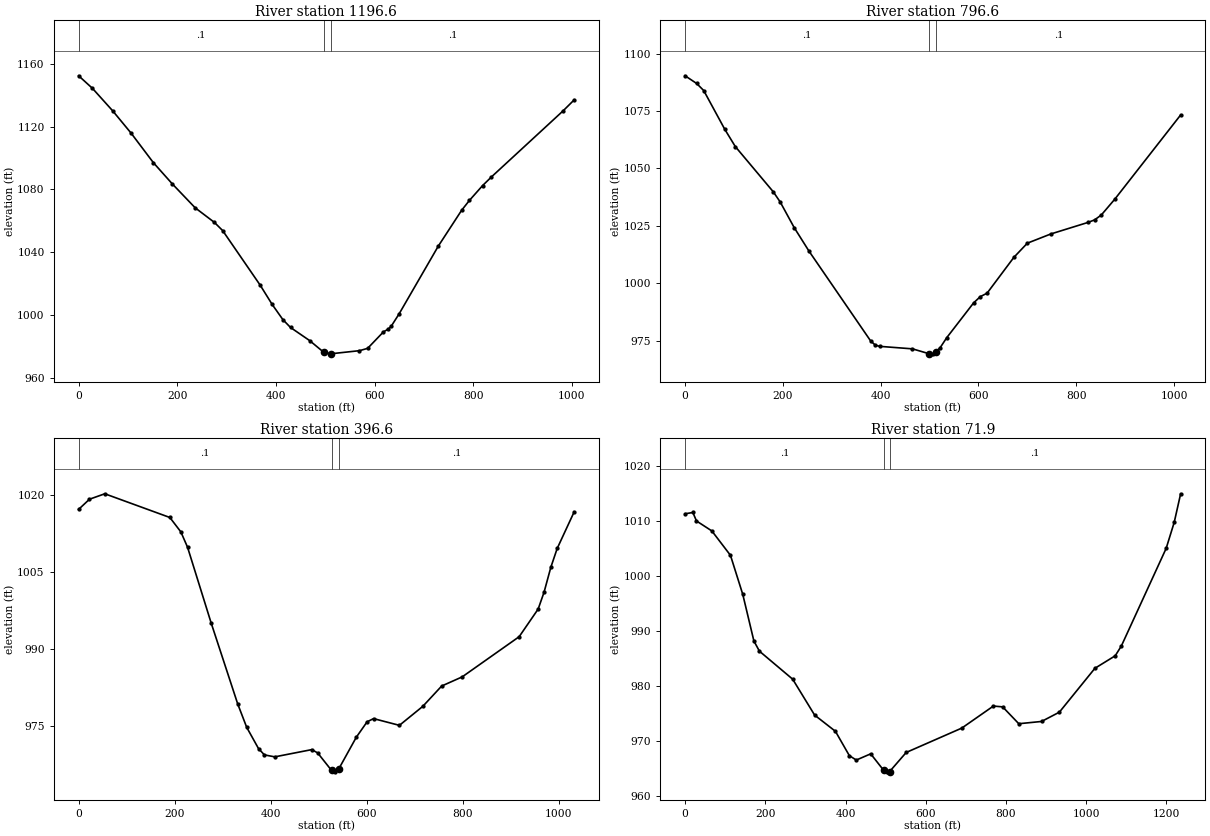
Type RM Length L Ch R = 1 ,1196.6,402.028,400,395.745
XS GIS Cut Line= 3
     1695572.626      299627.728     1695960.131      299950.149
     1696334.939      300281.888
#Sta/Elev= 30
       0 1152.28    28.1 1144.26    69.1 1129.96   106.3 1115.82   151.6 1096.98
   190.0 1083.47   236.2 1068.31   275.2 1059.02   291.9 1053.84   367.9 1019.16
   392.4 1006.80   414.2  997.11   429.6  992.16   468.2  983.86   496.6  976.47
   510.4  975.40   511.6  975.45   569.3  977.41   585.9  978.89   617.9  989.36
   628.1  991.22   633.8  993.01   649.6 1000.77   729.2 1043.96   776.5 1066.74
   792.3 1073.02   818.8 1082.38   836.7 1087.88   982.6 1130.10  1004.6 1136.95
#Mann= 3 , 0 , 0
       0     0.1       0   496.6   0.045       0   511.6     0.1       0
Bank Sta=   496.6,   511.6
Exp/Cntr=0.3,0.1

Type RM Length L Ch R = 1 ,796.6,408.835,400,396.362
XS GIS Cut Line= 3
     1695325.095      299995.226     1695747.178      300274.364
     1696185.554      300529.954
#Sta/Elev= 30
       0 1090.33    23.7 1086.97    38.1 1083.90    81.2 1067.02   102.7 1059.52
   180.3 1039.85   194.5 1035.41   223.0 1024.30   253.3 1014.05   379.6  974.90
   389.3  973.07   397.9  972.58   465.0  971.49   498.5  969.40   500.7  969.32
   507.6  969.32   513.5  970.33   521.4  971.91   535.1  976.35   590.1  991.50
   603.8  994.22   617.6  995.71   672.5 1011.33   700.0 1017.48   747.9 1021.48
   823.7 1026.49   837.5 1027.61   851.2 1029.73   878.7 1036.59  1013.5 1073.27
#Mann= 3 , 0 , 0
       0     0.1       0   498.5   0.045       0   513.5     0.1       0
Bank Sta=   498.5,   513.5
Exp/Cntr=0.3,0.1

Type RM Length L Ch R = 1 ,396.6,319.106,324.698,321.82
XS GIS Cut Line= 3
     1695114.298      300444.663     1695629.271      300586.978
     1696077.176      300804.499
#Sta/Elev= 30
       0 1017.29    22.6 1019.27    54.5 1020.33   190.0 1015.71   212.9 1012.91
   226.9 1009.91   276.2  995.11   331.4  979.37   350.1  974.82   374.7  970.68
   387.0  969.45   408.6  969.07   485.6  970.48   497.9  969.84   526.8  966.43
   534.3  966.15   541.8  966.71   578.5  972.91   600.9  975.90   614.3  976.52
   668.2  975.21   716.9  978.91   756.2  982.87   798.9  984.65   917.6  992.48
   957.2  997.87   969.4 1001.13   983.6 1006.01   996.8 1009.67  1032.2 1016.81
#Mann= 3 , 0 , 0
       0     0.1       0   526.8   0.045       0   541.8     0.1       0
Bank Sta=   526.8,   541.8
Exp/Cntr=0.3,0.1

Type RM Length L Ch R = 1 ,71.9,82.992,71.934,68.7
XS GIS Cut Line= 3
     1695043.246      300599.484     1695473.467      300855.844
     1696162.832      301109.640
#Sta/Elev= 30
       0 1011.29    19.4 1011.52    28.4 1009.98    66.7 1008.17   113.1 1003.74
   143.8  996.64   171.5  988.18   185.3  986.33   268.2  981.24   322.9  974.72
   374.8  971.77   409.5  967.35   426.8  966.55   462.7  967.68     495  964.69
   503.0  964.41     510  964.47   551.2  967.93   689.9  972.36   768.6  976.36
   791.7  976.21   831.9  973.15   888.6  973.56   933.1  975.25  1021.7  983.22
  1072.3  985.49  1087.6  987.27  1199.4 1005.02  1219.4 1009.74  1235.4 1014.92
#Mann= 3 , 0 , 0
       0     0.1       0     495   0.045       0     510     0.1       0
Bank Sta=     495,     510
Exp/Cntr=0.3,0.1